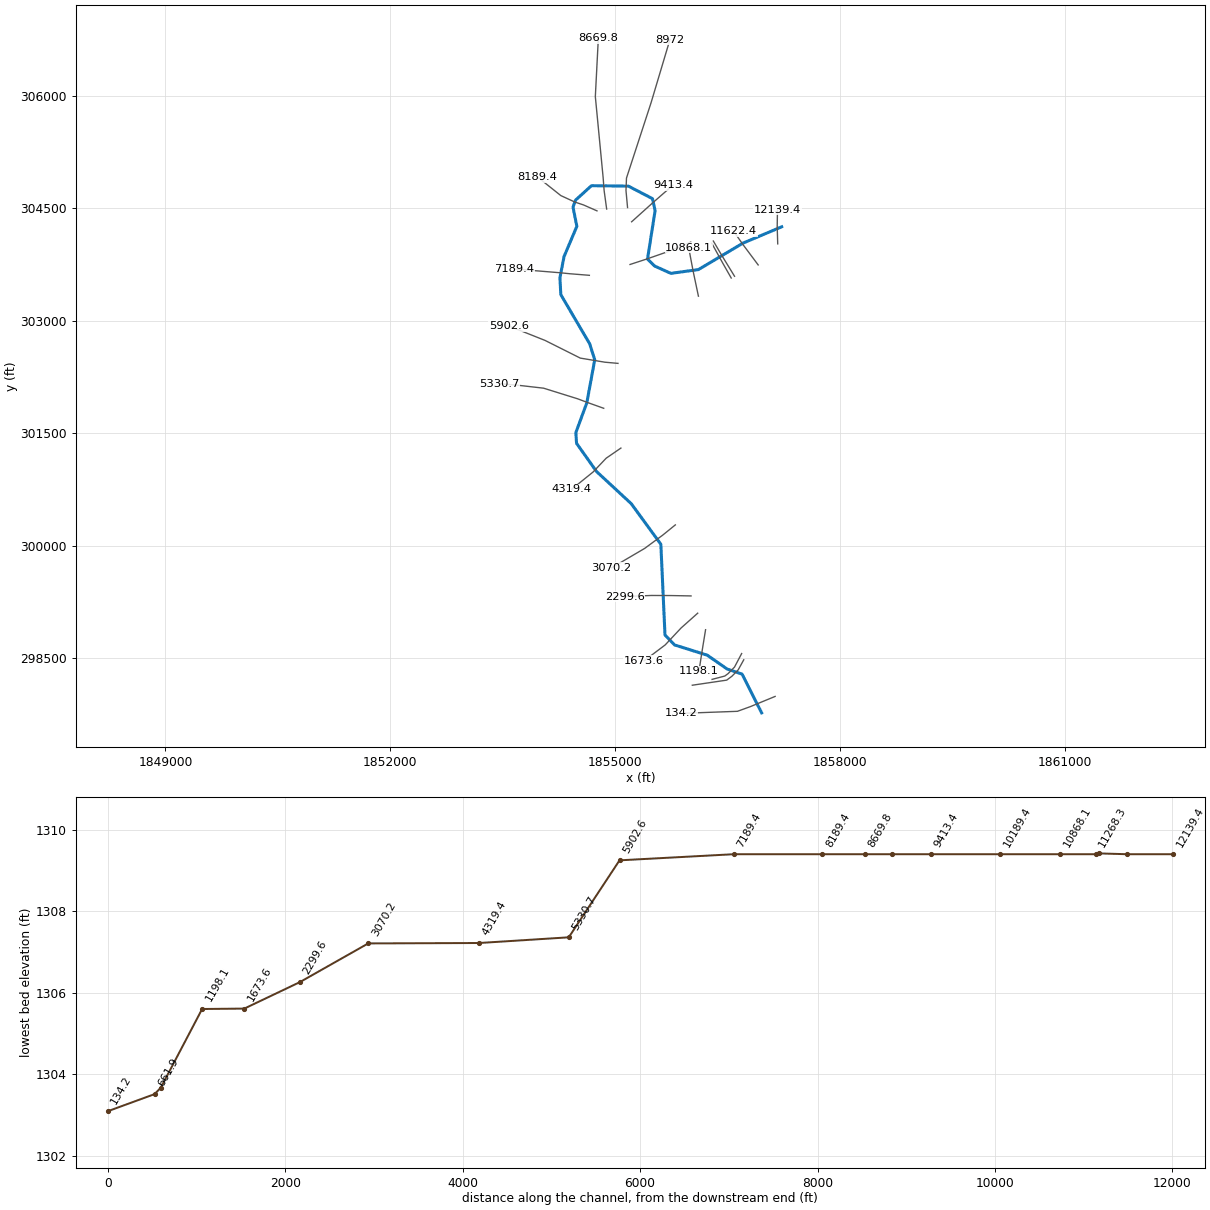
--- LitSandyCk.prj (project) ---

Proj Title=LitSandyCk
Current Plan=p01
Default Exp/Contr=0,0
English Units
Geom File=g01
Flow File=f01
Plan File=p01
BEGIN DESCRIPTION:
END DESCRIPTION:
DSS Export Rating Curves= 0
DSS Export Rating Curve Sorted= 0
DSS Export Volume Flow Curves= 0
DXF OffsetX= 0
DXF OffsetY= 0
DXF ScaleX= 0
DXF ScaleY= 0

--- LitSandyCk.p01 (plan) ---

Plan Title=Floodplain
Program Version=4.00
Geom File=g01
Flow File=f01
K Sum by GR=0
Std Step Tol=0.01
Critical Tol=0.01
Num of Std Step Trials=20
Max Error Tol=0.3
Flow Tol Ratio=0.001
Split Flow NTrial=30
Split Flow Tol=0.02
Split Flow Ratio=0.02
Log Output Level=0
Friction Slope Method=1
Unsteady Friction Slope Method=2
Unsteady Bridges Friction Slope Method=1
Global Log Level=0
CheckData=False
Run HTab=0
Run UNet=0
Run PostProcess=0
UNET Theta=0
UNET Theta Warmup=0
UNET ZTol=0
UNET ZSATol=0
UNET MxIter=0
UNET MaxInSteps=0
UNET DtIC=0
UNET DtMin=0
UNET MaxCRTS=0
UNET WFStab=0
UNET SFStab=0
UNET WFX=0
UNET SFX=0
UNET DSS MLevel=0
UNET DZMax Abort=0
UNET Convert EG Bridges=0
UNET Use Existing IB Tables=0
UNET Froude Limit=0
UNET Froude Power=0
Write IC File=0
Echo Input=False
Echo Output=False
Write Detailed=0

--- LitSandyCk.f01 (steady flow) ---

Flow Title=NFF Regression Equation
Program Version=4.10
Number of Profiles= 1
Profile Names=P100yr
River Rch & RM=LitSandyCk,Main            ,12139.4
    4300
River Rch & RM=LitSandyCk,Main            ,8972
    4327
River Rch & RM=LitSandyCk,Main            ,8669.8
    4889
River Rch & RM=LitSandyCk,Main            ,134.2
    5159
Boundary for River Rch & Prof#=LitSandyCk,Main            , 1
Up Type= 0
Dn Type= 3
Dn Slope=0.00226
DSS Import GetInterval= 0
DSS Import GetPeak= 0
DSS Import FillOption= 0

--- LitSandyCk.g01 (geometry) ---

Geom Title=USGS 10m DEM
Program Version=4.10

River Reach=LitSandyCk      ,Main
Reach XY= 30
     1857218.982      304253.649     1856702.255      304035.745
     1856108.503      303683.499     1855741.025      303632.896
     1855523.564      303730.903     1855429.599      303823.688
     1855530.694       304469.69     1855496.105      304628.835
     1855174.497      304796.028     1854681.655      304801.719
     1854469.462      304609.058     1854435.781      304515.832
     1854487.108      304260.194     1854316.272      303856.456
      1854261.22      303574.624     1854273.109      303349.514
      1854658.69      302692.335     1854725.517      302481.074
     1854619.924      301906.568     1854473.514      301509.543
     1854483.287      301366.097     1854749.553      300991.043
     1855212.905      300561.479     1855607.205      300021.214
     1855662.551      298811.298     1855789.741      298678.926
     1856226.347      298541.933     1856491.097      298357.777
     1856690.584      298289.571     1856951.451      297772.881

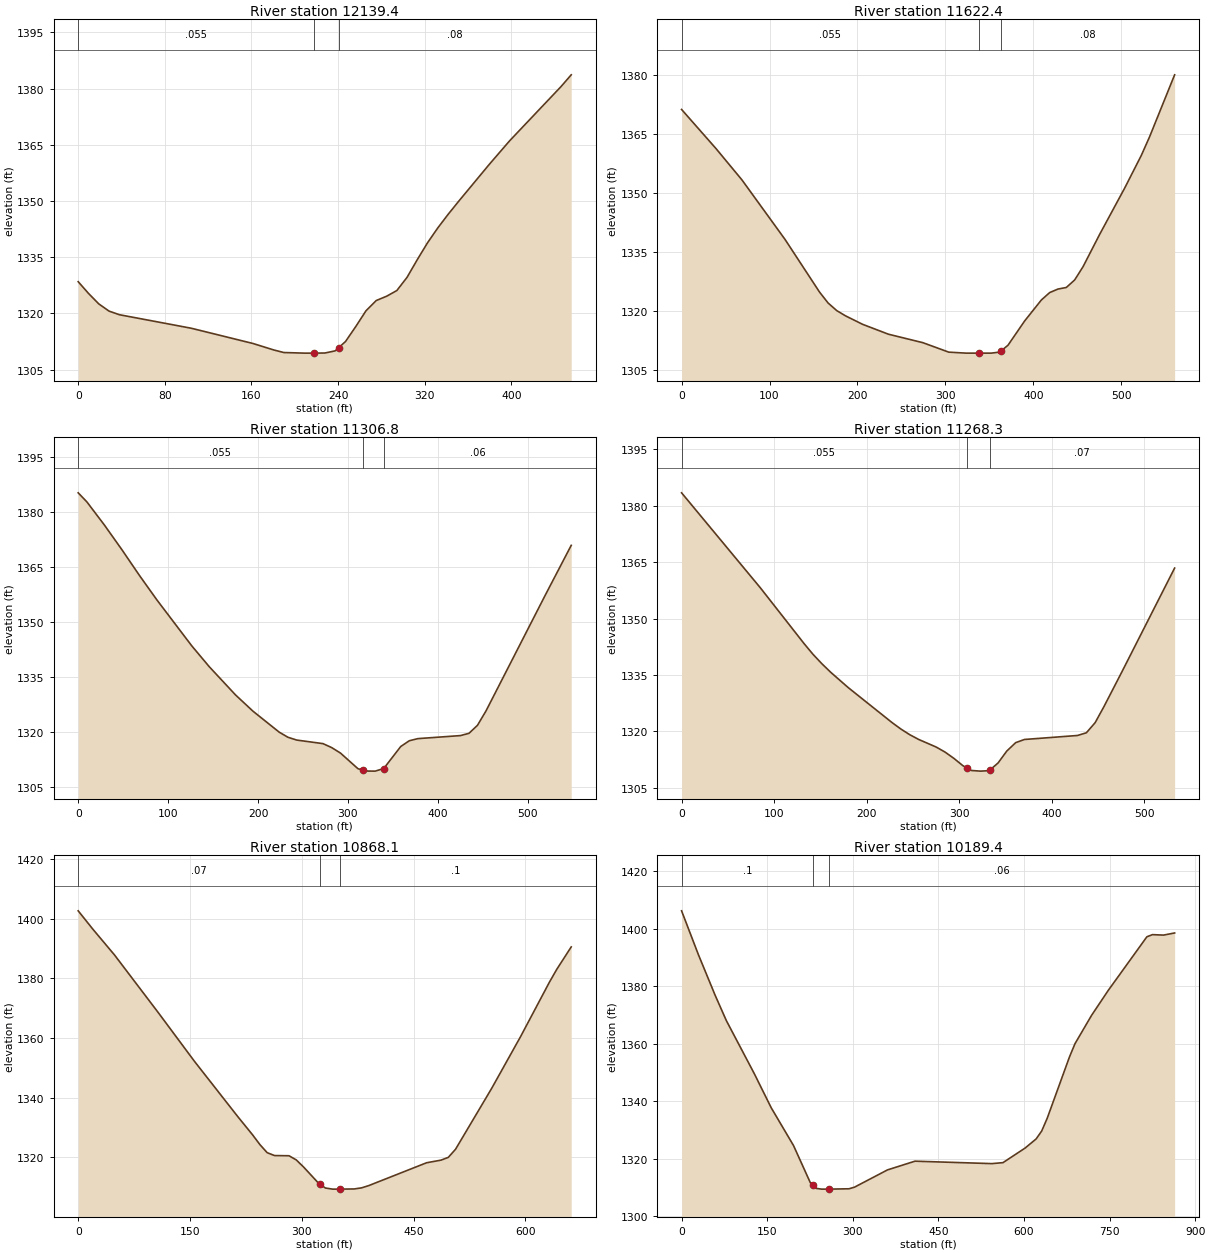
Type RM Length L Ch R = 1 ,12139.4 ,503.8,516.9,531
XS GIS Cut Line= 3
     1857166.036      304026.114      1857159.07      304253.816
     1857162.851       304481.23
#Sta/Elev= 30
       0 1328.46     9.5 1325.34      19 1322.54    28.5 1320.61      38 1319.65
   104.4 1316.04   161.4 1311.97   180.4 1310.26   189.8 1309.56   208.8  1309.4
   217.8  1309.4   227.8 1309.43   237.3 1310.01  240.67  1310.9   246.8 1312.49
   256.2 1316.46   265.7 1320.69   275.2 1323.44   284.7 1324.57   294.2  1326.1
   303.6 1329.61   313.1 1334.35   322.6 1338.87     332  1342.8   341.5 1346.41
     351 1349.81   379.4 1359.71   398.4 1366.07   445.8 1380.52   455.2 1383.65
#Mann= 3 , 0 , 0
       0    .055       0   217.8    .045       0  240.67     .08       0
Bank Sta=217.8,240.67
XS Rating Curve= 0 ,0
Exp/Cntr=0.3,0.1

Type RM Length L Ch R = 1 ,11622.4 ,317.2,315.6,313.8
XS GIS Cut Line= 3
      1856905.31      303745.293     1856705.794      304012.338
     1856575.258      304198.662
#Sta/Elev= 30
       0 1371.24    39.2  1361.3    68.6 1353.38   117.6 1338.28   156.9  1324.9
   166.7 1322.11   176.5 1320.19   186.3 1318.88   205.9 1316.71   235.3  1314.2
   274.5 1312.05   303.9 1309.65   323.5  1309.4  337.85  1309.4   352.3  1309.4
   361.8 1309.66     363 1309.88   371.3 1311.41   390.2 1317.56   409.2 1322.88
   418.7 1324.77   428.1 1325.66   437.6 1326.06   447.1 1327.97   456.6 1331.32
   475.5 1339.52     504 1351.29   522.9 1359.57   532.4 1364.34   560.8 1380.03
#Mann= 3 , 0 , 0
       0    .055       0  337.85    .045       0     363     .08       0
Bank Sta=337.85,363
XS Rating Curve= 0 ,0
Exp/Cntr=0.3,0.1

Type RM Length L Ch R = 1 ,11306.8 ,39.4,38.5,37.9
XS GIS Cut Line= 3
     1856590.206      303594.251     1856422.591      303867.807
     1856307.301       304063.93
#Sta/Elev= 30
       0  1385.3     9.7 1382.82    29.2  1376.5    48.6  1369.8      68 1362.82
    87.5 1356.11   126.4 1343.55   145.8 1337.88     175 1330.19   194.4 1325.76
   223.6 1320.04   233.3 1318.65     243 1317.89   272.2 1316.92   281.9 1315.84
   291.7 1314.34   311.1 1310.09   316.3 1309.72   320.8 1309.44   330.3 1309.42
   339.8 1310.13   358.7 1316.13   368.2  1317.7   377.7 1318.28   425.1 1319.11
   434.6 1319.73     444  1321.9   453.5 1325.82   519.9 1357.62   548.3 1370.98
#Mann= 3 , 0 , 0
       0    .055       0   316.3    .045       0   339.8     .06       0
Bank Sta=316.3,339.8
XS Rating Curve= 0 ,0
Exp/Cntr=0.3,0.1

Type RM Length L Ch R = 1 ,11268.3 ,406.7,400.2,392.8
XS GIS Cut Line= 3
     1856545.935      303570.814     1856433.377      303768.518
     1856285.511       304035.91
#Sta/Elev= 30
       0 1383.43    85.3 1358.12   132.7 1343.24   142.2 1340.44   151.7 1337.96
   161.2  1335.7   180.1 1331.63   227.5 1322.32     237 1320.61   246.6  1319.1
   256.2 1317.84   275.2 1315.81   284.8 1314.47   294.3 1312.81   303.9 1310.89
  308.48 1310.22   313.4 1309.57     323  1309.4   332.5 1309.52  333.34  1309.7
   342.1 1311.56   351.6 1314.75   361.2 1316.98   370.7 1317.82     428 1318.88
   437.6  1319.6   447.1  1322.3   456.7 1326.61   475.8 1335.71     533 1363.41
#Mann= 3 , 0 , 0
       0    .055       0  308.48    .045       0  333.34     .07       0
Bank Sta=308.48,333.34
XS Rating Curve= 0 ,0
Exp/Cntr=0.3,0.1

Type RM Length L Ch R = 1 ,10868.1 ,711.9,678.7,646.5
XS GIS Cut Line= 3
     1856108.435      303328.626     1856037.826      303662.512
     1855978.227      303977.064
#Sta/Elev= 30
       0 1402.57    19.5 1396.48    48.8 1387.77   107.3 1368.54     156 1352.18
   214.5 1333.55     234 1327.56   243.8  1324.3   253.5 1321.61   263.3 1320.64
   282.8 1320.57   292.5 1319.19   302.3 1316.82   321.8 1311.56   324.5 1311.05
   331.5 1309.78   341.3  1309.4     351  1309.4   370.4 1309.46   380.1 1309.82
   389.8 1310.58   467.4 1318.23   486.8 1319.11   496.5 1320.03   506.2 1322.74
   554.7 1343.14   593.5 1360.48   632.3 1378.75     642 1382.98   661.4 1390.49
#Mann= 3 , 0 , 0
       0     .07       0   324.5    .045       0     351      .1       0
Bank Sta=324.5,351
XS Rating Curve= 0 ,0
Exp/Cntr=0.3,0.1

Type RM Length L Ch R = 1 ,10189.4 ,766.6,776,784.2
XS GIS Cut Line= 4
     1855196.213      303751.272     1855429.304      303827.552
     1855720.232      303929.357     1856006.518      304049.517
#Sta/Elev= 30
       0 1406.29    29.4 1391.07    58.9 1376.85    78.5 1368.05   127.5 1349.57
     157 1337.75   196.2 1324.56   225.6 1311.64  230.17 1310.69   235.4 1309.68
   245.2  1309.4  258.48  1309.4   293.4 1309.52     303 1310.08   360.8 1316.09
     409 1319.13   543.8 1318.28   563.2 1318.62     602  1323.7   621.4 1326.89
   631.1 1329.64   640.8 1334.11   679.6 1355.34   689.3 1359.99   718.4 1369.88
   747.5 1378.53   815.4 1397.25   825.2    1398   844.6 1397.84     864 1398.58
#Mann= 3 , 0 , 0
       0      .1       0  230.17    .045       0  258.48     .06       0
Bank Sta=230.17,258.48
XS Rating Curve= 0 ,0
Exp/Cntr=0.3,0.1

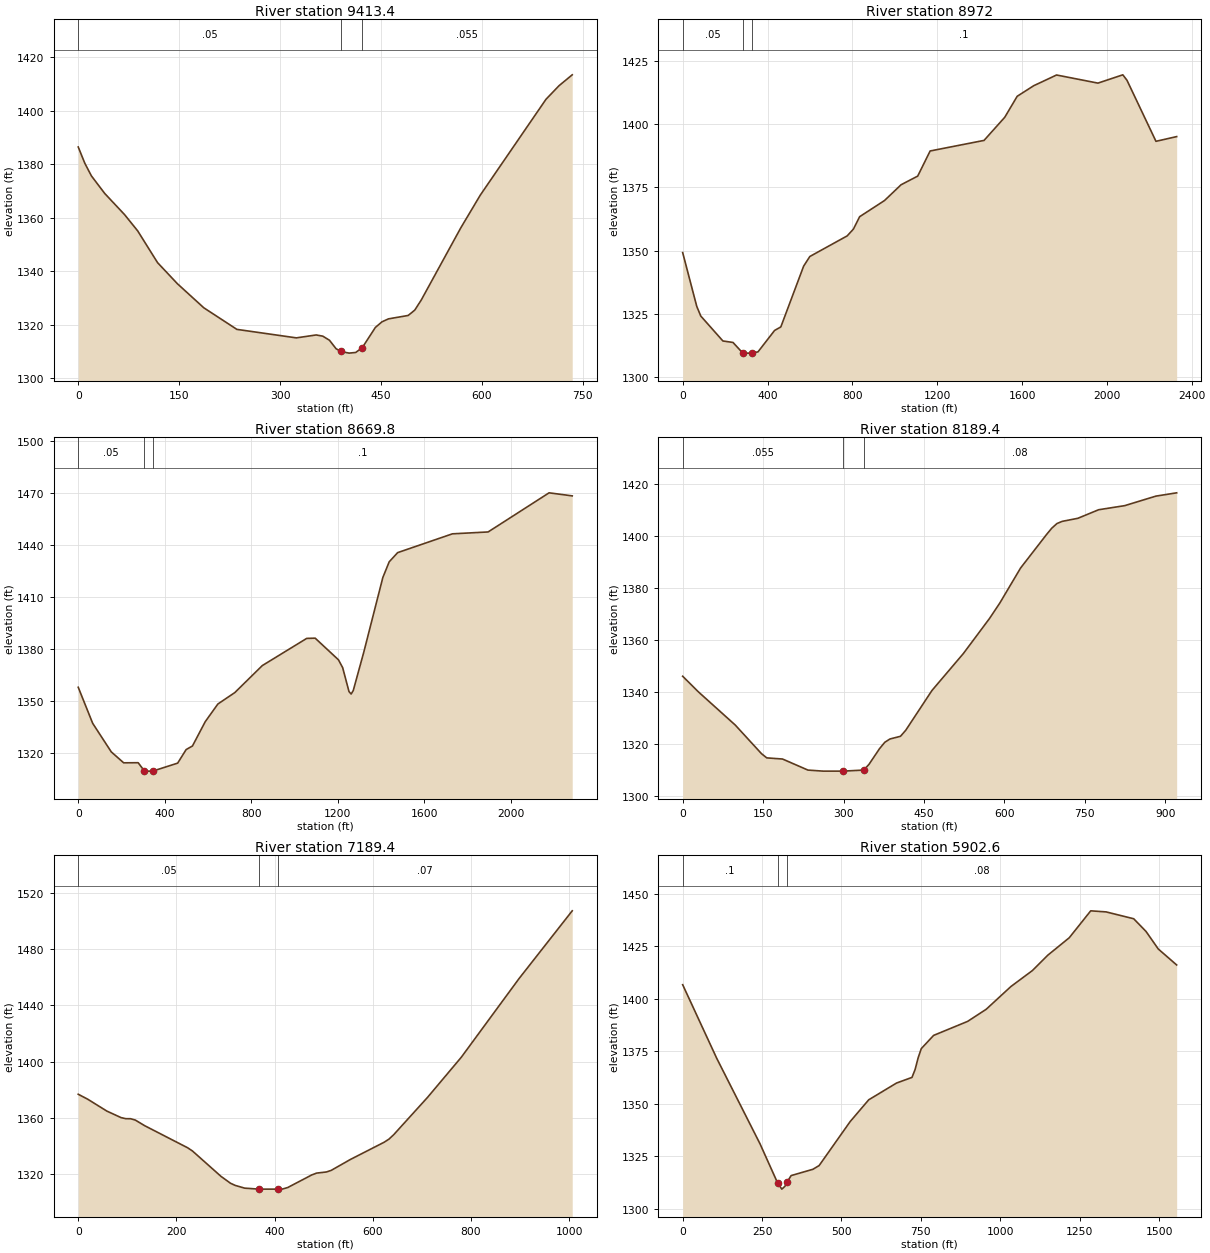
Type RM Length L Ch R = 1 ,9413.4  ,423,441.5,459.7
XS GIS Cut Line= 3
      1855217.81      304320.814     1855495.378      304570.513
     1855767.289      304807.793
#Sta/Elev= 30
       0  1386.4     9.8 1380.32    19.6  1375.6    39.3 1369.06    68.8 1361.16
    88.4 1355.05   117.9  1343.2   147.4 1335.32   186.7 1326.32   235.8 1318.27
   324.2  1315.1   353.7 1316.19   363.5 1315.73   373.4 1314.21   383.1 1311.08
  389.84 1310.05   402.6  1309.4   412.4 1309.65   422.1 1311.42   441.6 1318.99
   451.4 1321.09   461.1  1322.2   490.4 1323.47   500.2 1325.48   509.9 1329.28
   568.4 1356.12   597.7 1368.48   695.2 1404.22   714.7 1409.32   734.2 1413.36
#Mann= 3 , 0 , 0
       0     .05       0  389.84    .045       0   422.1    .055       0
Bank Sta=389.84,422.1
XS Rating Curve= 0 ,0
Exp/Cntr=0.3,0.1

Type RM Length L Ch R = 1 ,8972    ,299.5,302.2,304.9
XS GIS Cut Line= 5
     1855163.227      304510.169     1855142.394      304736.732
     1855148.904      304903.398     1855476.628      305907.214
     1855728.364      306749.228
#Sta/Elev= 30
       0 1349.17    66.4 1327.89    85.3 1324.08   189.6 1314.21   237.3 1313.62
   283.4 1309.42   286.4  1309.4   325.6  1309.4   355.1  1309.9   433.4 1318.38
   462.8 1319.77   570.3 1343.82   599.6 1347.64   775.6 1355.79     805 1358.48
   834.3 1363.38   951.6 1369.78  1029.8 1376.03  1108.1 1379.44  1166.7 1389.39
  1420.9 1393.57  1518.6 1402.73  1577.2 1411.03  1655.3 1415.22  1762.8 1419.45
    1958 1416.24  2075.2 1419.52  2094.8 1417.38  2231.5 1393.21  2329.1 1395.08
#Mann= 3 , 0 , 0
       0     .05       0   283.4    .045       0   325.6      .1       0
Bank Sta=283.4,325.6
XS Rating Curve= 0 ,0
Exp/Cntr=0.3,0.1

Type RM Length L Ch R = 1 ,8669.8  ,453.6,480.4,504.6
XS GIS Cut Line= 5
     1854884.581      304490.638     1854850.727      304736.732
     1854837.706      304908.607     1854733.504      305989.589
     1854773.503      306766.589
#Sta/Elev= 30
       0 1357.83    66.9    1337   152.9  1320.5   210.2  1314.2   277.1 1314.26
   305.9 1309.54   315.4  1309.4   344.2  1309.4   459.9 1314.02     499 1321.84
   528.4 1323.94   587.1  1337.9   645.8 1348.16   724.1 1354.76   851.3 1370.36
  1056.7 1386.06  1095.9  1386.2  1203.5 1373.71    1223 1369.19  1252.4 1355.32
  1262.2 1353.95    1272 1355.93  1320.9 1378.21  1408.9 1421.26  1438.3  1430.3
  1477.4 1435.61  1730.5 1446.46  1895.8 1447.55  2177.8 1470.15  2284.8 1468.39
#Mann= 3 , 0 , 0
       0     .05       0   305.9    .045       0   344.2      .1       0
Bank Sta=305.9,344.2
XS Rating Curve= 0 ,0
Exp/Cntr=0.3,0.1

Type RM Length L Ch R = 1 ,8189.4  ,994.9,1000,1007.9
XS GIS Cut Line= 5
      1854755.57      304466.213     1854576.158      304545.161
     1854460.363      304583.874     1854273.779      304669.494
     1853962.602      304917.168
#Sta/Elev= 30
       0 1345.92    29.4 1339.89      98 1327.14     147 1316.11   156.8  1314.5
   186.2 1314.06   233.6  1309.8   261.8  1309.4   299.3  1309.4   337.7 1309.81
   347.4 1312.01     367 1318.03   376.8 1320.49   386.5 1321.77   406.1 1322.81
   415.9 1325.12   464.8 1340.44   523.4 1354.67   571.9 1368.09   591.3 1374.09
   630.1 1387.59   678.6 1400.51   688.3 1402.93     698 1404.71   707.7 1405.54
   736.8 1406.71   775.6 1410.01   824.1 1411.58   882.3 1415.25   921.1 1416.52
#Mann= 3 , 0 , 0
       0    .055       0   299.3    .045       0   337.7     .08       0
Bank Sta=299.3,337.7
XS Rating Curve= 0 ,0
Exp/Cntr=0.3,0.1

Type RM Length L Ch R = 1 ,7189.4  ,1288.2,1286.9,1284.9
XS GIS Cut Line= 4
     1854654.008      303606.838     1854393.086      303627.907
     1854267.929      303640.629     1853651.107      303691.329
#Sta/Elev= 30
       0 1376.78    19.4 1373.24    58.2 1364.84    87.3 1360.18      97 1359.42
   106.6  1359.4   116.3 1358.44   135.7 1354.39     223 1338.75   232.7  1336.5
   290.8 1318.49   310.2 1313.58   319.8 1312.04   339.2 1310.09   368.2  1309.4
   407.2  1309.4     417 1309.54   426.9 1310.55     476 1319.51   485.8 1320.79
   505.5 1321.57   515.3 1322.69   554.6 1330.48   623.4 1342.72   633.2 1344.94
     643 1348.14   711.8  1374.6   780.5 1403.07   898.4 1459.04  1006.5 1507.04
#Mann= 3 , 0 , 0
       0     .05       0   368.2    .045       0   407.2     .07       0
Bank Sta=368.2,407.2
XS Rating Curve= 0 ,0
Exp/Cntr=0.3,0.1

Type RM Length L Ch R = 1 ,5902.6  ,575.8,571.9,567.6
XS GIS Cut Line= 5
     1855035.518      302432.793     1854861.039      302448.418
     1854532.914      302503.105      1854063.07       302738.75
      1853578.19      302931.693
#Sta/Elev= 30
       0 1406.72     107 1371.69   243.7 1330.79  299.02 1312.14   312.2 1309.25
   321.9 1310.59  327.88 1312.46   341.5 1315.71     410 1318.71   429.6 1320.49
   527.3 1341.46   585.7 1351.84   673.3 1359.84     722 1362.53   731.7 1366.27
   741.4 1371.88   751.2 1376.25   790.1 1382.56   897.2 1389.24   955.6 1395.01
  1033.4 1405.86  1101.1 1413.48  1149.4 1420.78  1217.1 1429.12  1284.7 1441.96
    1333 1441.45    1420 1438.18  1458.7 1432.15  1497.3 1423.78  1555.3 1416.14
#Mann= 3 , 0 , 0
       0      .1       0  299.02    .045       0  327.88     .08       0
Bank Sta=299.02,327.88
XS Rating Curve= 0 ,0
Exp/Cntr=0.3,0.1

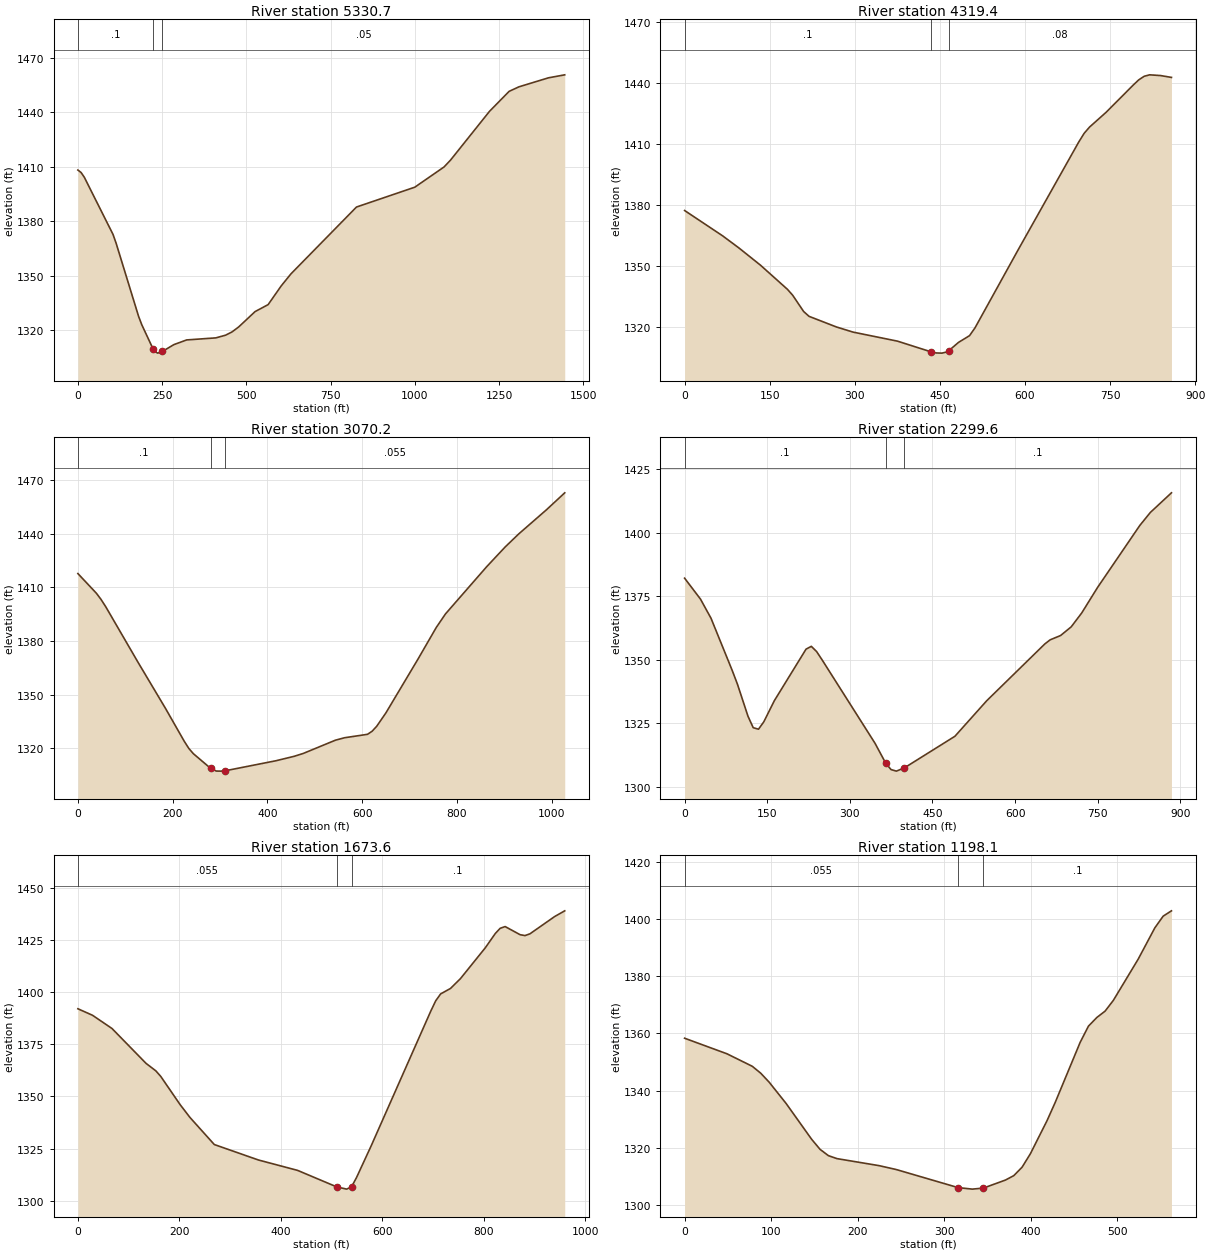
Type RM Length L Ch R = 1 ,5330.7  ,985,1011.3,1037.7
XS GIS Cut Line= 6
     1854845.414      301833.835     1854631.165      301910.342
     1854497.359      301960.476     1854043.331      302102.064
     1853728.299      302138.067     1853447.982      302163.464
#Sta/Elev= 30
       0 1408.16     9.5  1406.8      19 1404.22   104.3  1372.7   113.8 1367.66
   180.1 1327.61   189.6 1322.99  223.82 1309.37   227.5 1308.25     237 1307.36
  250.93 1308.31   284.7 1312.03   322.8 1314.63   409.2 1315.75   438.3 1317.24
   457.7 1319.08   477.2 1321.79   525.7 1330.22   564.5 1334.07   603.3 1344.38
   632.4 1351.04   826.6 1387.79   999.7 1398.72  1086.2 1409.82  1105.4 1413.57
  1221.3 1440.48  1279.5 1451.48  1308.6 1453.97    1396 1458.92  1444.5 1460.58
#Mann= 3 , 0 , 0
       0      .1       0  223.82    .045       0  250.93     .05       0
Bank Sta=223.82,250.93
XS Rating Curve= 0 ,0
Exp/Cntr=0.3,0.1

Type RM Length L Ch R = 1 ,4319.4  ,1253,1249.2,1245
XS GIS Cut Line= 4
     1855074.581      301303.453     1854878.116      301168.431
     1854703.053      300984.008     1854418.331      300754.841
#Sta/Elev= 30
       0 1377.37    66.8 1364.96    95.4 1359.03   133.5 1350.54   181.2 1338.63
   190.7 1335.63   209.8 1327.71   219.3 1325.32   267.7 1320.08   297.1 1317.55
   375.3 1313.11     434 1307.89   443.8  1307.3   453.6 1307.22   463.3 1307.86
  465.72 1308.42   482.9 1312.51   502.3 1315.82   511.9 1319.64   588.8 1358.45
   694.6 1410.97   704.3 1415.33   713.9 1418.43   742.7  1425.6   790.8 1439.06
   800.4  1441.6   810.1 1443.39   819.7 1444.11   838.9 1443.75   858.2 1442.84
#Mann= 3 , 0 , 0
       0      .1       0     434    .045       0  465.72     .08       0
Bank Sta=434,465.72
XS Rating Curve= 0 ,0
Exp/Cntr=0.3,0.1

Type RM Length L Ch R = 1 ,3070.2  ,785.2,770.6,756.3
XS GIS Cut Line= 4
     1855800.275      300279.147     1855633.608       300143.73
     1855392.083       299966.02     1854949.581       299706.23
#Sta/Elev= 30
       0 1417.79      39 1406.78    48.8 1403.33    58.6 1399.31   126.9 1368.15
   185.5 1342.07   224.4 1323.99   234.1 1319.95   243.8 1316.96  280.06  1308.8
   292.1 1307.25   301.8 1307.21   311.5 1307.43   417.9 1313.01   456.6  1315.5
   475.9 1317.12   543.6 1324.52     563  1325.9   611.4 1327.81   621.1 1329.54
   630.8 1332.31   650.2  1339.8   717.9 1369.89   756.6 1387.64     776 1395.21
   863.1 1421.67   901.9 1432.65   930.9 1440.04     989 1453.45  1027.7 1462.97
#Mann= 3 , 0 , 0
       0      .1       0  280.06    .045       0   311.5    .055       0
Bank Sta=280.06,311.5
XS Rating Curve= 0 ,0
Exp/Cntr=0.3,0.1

Type RM Length L Ch R = 1 ,2299.6  ,607.4,626,644.4
XS GIS Cut Line= 4
     1856010.254      299332.116     1855741.816      299337.077
     1855480.831      299338.175     1855126.664      299324.286
#Sta/Elev= 30
       0 1382.09    28.8 1373.88    47.9 1366.37    86.3 1345.91    95.9 1340.46
   115.1 1327.82   124.6 1323.33   134.2 1322.74   143.8 1325.64     163 1333.96
   220.5  1354.2   230.1  1355.3   239.7 1353.24   249.3  1350.1   345.8 1317.18
   365.2 1309.36   374.8 1306.87   384.5 1306.26   399.1 1307.55   490.8 1319.96
   548.6 1333.94     654 1356.24   663.6 1357.85   682.7 1359.56   701.9 1362.96
   721.1 1368.45   749.8 1378.46   826.4 1402.79   845.6 1407.92   883.9 1415.63
#Mann= 3 , 0 , 0
       0      .1       0   365.2    .045       0   399.1      .1       0
Bank Sta=365.2,399.1
XS Rating Curve= 0 ,0
Exp/Cntr=0.3,0.1

Type RM Length L Ch R = 1 ,1673.6  ,462,475.5,489.1
XS GIS Cut Line= 4
     1856098.886      299102.064     1855876.664      298904.147
     1855664.858      298678.453     1855383.608      298466.647
#Sta/Elev= 30
       0 1392.03    28.8 1388.91    67.2 1382.57   134.4 1365.84   153.6 1362.28
   163.2 1359.64   201.6 1346.04   220.8 1339.96   268.8 1326.97   355.6 1319.58
     433 1314.58   510.4 1306.64   529.7 1305.61   539.4 1306.81   549.1 1311.22
   578.1 1326.48   695.1  1390.8   704.9  1395.8   714.7 1399.14   734.2 1401.77
   753.8 1406.48   802.7 1421.24   822.3 1428.05     832 1430.58   841.8 1431.41
   871.2 1427.52   880.9 1427.09   890.7 1427.94   939.6 1436.25   959.2 1438.95
#Mann= 3 , 0 , 0
       0    .055       0   510.4    .045       0   539.4      .1       0
Bank Sta=510.4,539.4
XS Rating Curve= 0 ,0
Exp/Cntr=0.3,0.1

Type RM Length L Ch R = 1 ,1198.1  ,480.6,465.1,449.2
XS GIS Cut Line= 3
     1856203.831      298881.596     1856150.275      298553.453
     1856115.553      298326.022
#Sta/Elev= 30
       0  1358.3    48.9 1352.87    78.2  1348.5      88 1346.08    97.8 1342.92
   117.4 1335.48   146.7 1323.05   156.5  1319.5   166.2 1317.29     176 1316.26
   224.9 1313.79   244.5 1312.45  315.94 1306.14   332.5  1305.6  345.34 1305.97
   370.8 1308.77   380.4 1310.31     390 1313.26   399.6 1317.96   418.8 1329.49
   428.4 1335.97   457.1 1356.85   466.7 1362.52   476.3 1365.52   485.9 1367.76
   495.4 1371.49   524.2 1385.93   543.4 1396.84     553 1400.92   562.6 1402.79
#Mann= 3 , 0 , 0
       0    .055       0  315.94    .045       0  345.34      .1       0
Bank Sta=315.94,345.34
XS Rating Curve= 0 ,0
Exp/Cntr=0.3,0.1

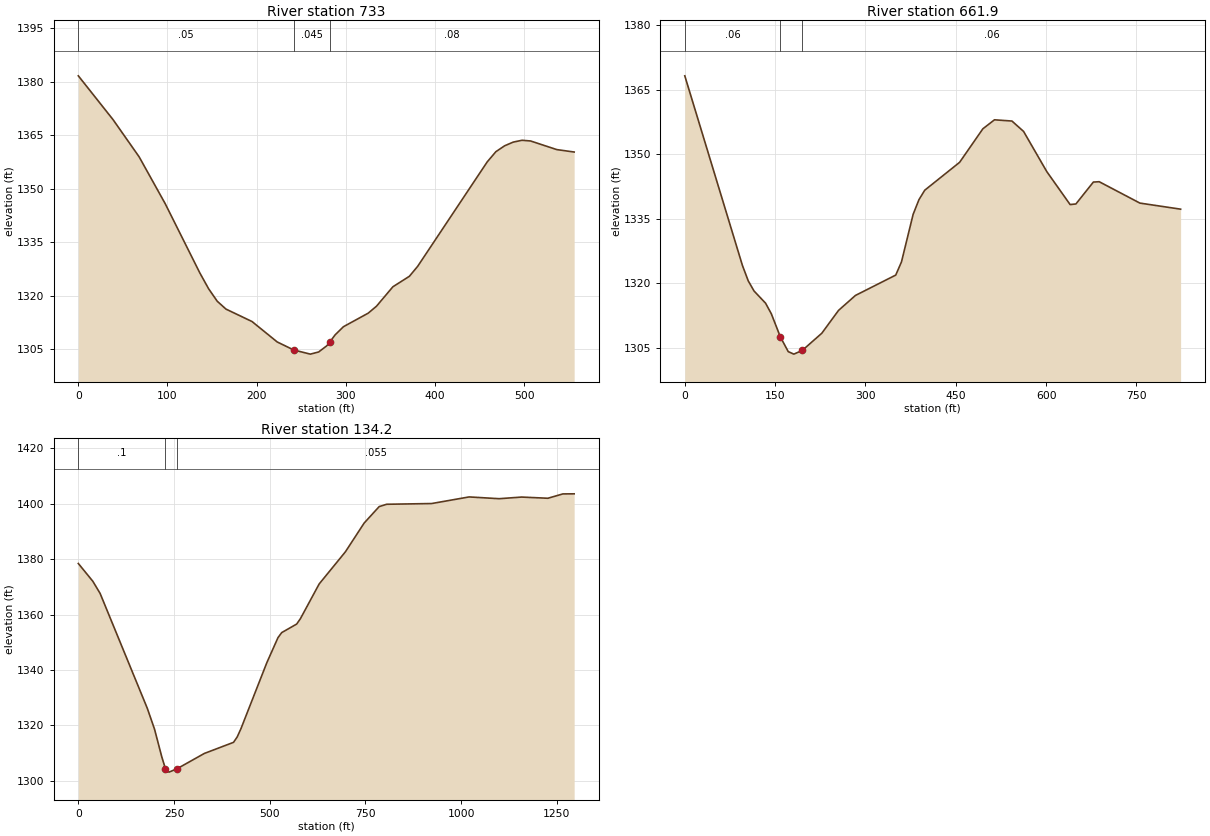
Type RM Length L Ch R = 1 ,733     ,69.5,71.1,72.7
XS GIS Cut Line= 5
     1856684.997      298563.869     1856589.551      298382.999
     1856504.916      298297.061     1856460.443      298263.966
     1856290.636      298219.486
#Sta/Elev= 30
       0 1381.61      39 1369.32    68.2 1358.92    97.4 1345.82   136.3  1326.4
   146.1 1321.99   155.8 1318.48   165.6 1316.28   194.8  1312.8   223.1 1307.07
   241.6 1304.83   260.2 1303.67   269.5 1304.27   278.7 1306.01  282.43 1307.19
     288 1309.06   297.3 1311.34   325.1 1315.14   334.4 1317.09   352.8 1322.53
   371.3 1325.47   380.6 1328.26   458.6 1357.51   468.3 1360.36   478.1 1362.01
   487.8 1363.05   497.6 1363.56   507.3 1363.36   536.6 1360.95   556.1 1360.27
#Mann= 3 , 0 , 0
       0     .05       0   241.6    .045       0  282.43     .08       0
Bank Sta=241.6,282.43
XS Rating Curve= 0 ,0
Exp/Cntr=0.3,0.1

Type RM Length L Ch R = 1 ,661.9   ,536.3,527.6,518.6
XS GIS Cut Line= 5
     1856713.249      298480.655      1856639.03      298346.541
     1856554.395      298260.603     1856485.455      298209.299
     1856026.917      298141.531
#Sta/Elev= 30
       0 1368.19    95.8 1324.08   105.4 1320.53     115 1318.18   134.1 1315.36
   143.7 1312.89   158.7 1307.51   171.8 1304.09   181.1 1303.51  194.99 1304.36
   227.5 1308.36   255.3 1313.67   283.4 1317.15   350.3 1321.88   359.8 1324.93
   379.2    1336   388.8 1339.39   398.5 1341.61   456.4 1348.09     495 1355.88
   514.3 1357.97   543.3 1357.68   562.6 1355.27   601.2 1345.92   639.9 1338.27
   649.5 1338.41   678.5  1343.5   688.2 1343.58   755.8 1338.61   823.4  1337.2
#Mann= 3 , 0 , 0
       0     .06       0   158.7    .045       0  194.99     .06       0
Bank Sta=158.7,194.99
XS Rating Curve= 0 ,0
Exp/Cntr=0.3,0.1

Type RM Length L Ch R = 1 ,134.2   ,134.2,134.2,134.2
XS GIS Cut Line= 5
       1857131.6      297992.088     1856921.194      297905.567
      1856801.46      297856.331     1856628.622      297793.556
     1855875.007      297766.097
#Sta/Elev= 30
       0 1378.44    37.9 1372.01    56.9 1367.63   180.1 1326.16   199.1 1318.57
     218 1308.59   227.5 1304.33   236.8 1303.09   257.4 1304.28   329.2 1309.84
   405.4 1313.85     415 1315.81   424.7 1318.77   492.5 1342.67   521.5 1351.67
   531.2 1353.48   570.2 1356.56     580  1358.5     629 1371.04   697.6 1382.67
   746.5 1393.04   785.7 1398.98   805.3 1399.83   922.8 1400.09  1020.7 1402.48
  1099.1 1401.84  1157.8 1402.43  1226.4    1402  1265.6 1403.57    1295  1403.6
#Mann= 3 , 0 , 0
       0      .1       0   227.5    .045       0   257.4    .055       0
Bank Sta=227.5,257.4
XS Rating Curve= 0 ,0
Exp/Cntr=0.3,0.1

Chan Stop Cuts=-1
Use User Specified Reach Order=0
Composite Channel Slope=5